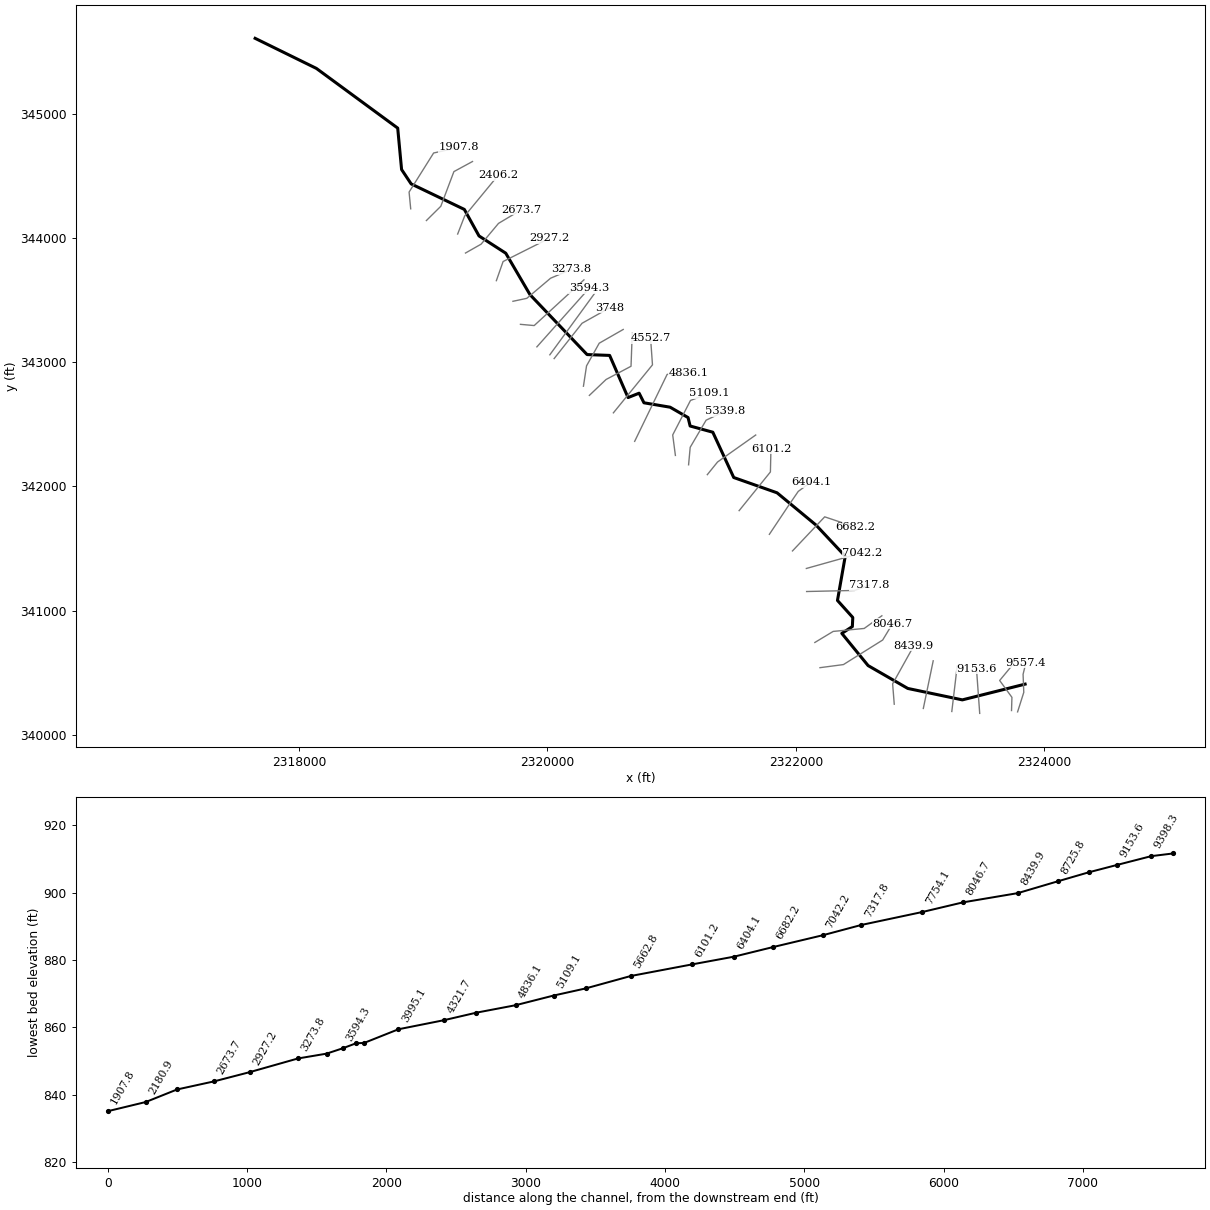
--- MFSCTRIB.prj (project) ---

Proj Title=MFSCTRIB
Current Plan=p01
Default Exp/Contr=0,0
English Units
Geom File=g01
Flow File=f01
Plan File=p01
BEGIN DESCRIPTION:
END DESCRIPTION:
DSS Export Rating Curves= 0
DSS Export Rating Curve Sorted= 0
DSS Export Volume Flow Curves= 0
DXF OffsetX= 0
DXF OffsetY= 0
DXF ScaleX= 0
DXF ScaleY= 0

--- MFSCTRIB.p01 (plan) ---

Plan Title=Floodplain
Program Version=4.00
Geom File=g01
Flow File=f01
K Sum by GR=0
Std Step Tol=0.01
Critical Tol=0.01
Num of Std Step Trials=20
Max Error Tol=0.3
Flow Tol Ratio=0.001
Split Flow NTrial=30
Split Flow Tol=0.02
Split Flow Ratio=0.02
Log Output Level=0
Friction Slope Method=1
Unsteady Friction Slope Method=2
Unsteady Bridges Friction Slope Method=1
Global Log Level=0
CheckData=False
Run HTab=0
Run UNet=0
Run PostProcess=0
UNET Theta=0
UNET Theta Warmup=0
UNET ZTol=0
UNET ZSATol=0
UNET MxIter=0
UNET MaxInSteps=0
UNET DtIC=0
UNET DtMin=0
UNET MaxCRTS=0
UNET WFStab=0
UNET SFStab=0
UNET WFX=0
UNET SFX=0
UNET DSS MLevel=0
UNET DZMax Abort=0
UNET Convert EG Bridges=0
UNET Use Existing IB Tables=0
UNET Froude Limit=0
UNET Froude Power=0
Write IC File=0
Echo Input=False
Echo Output=False
Write Detailed=0

--- MFSCTRIB.f01 (steady flow) ---

Flow Title=NFF Regression Equation
Program Version=4.00
Number of Profiles=1
Profile Names=P100yr
River Rch & RM=MFSCTRIB,Main      ,9557.4
479.1213
River Rch & RM=MFSCTRIB,Main      ,9398.3
479.5578
River Rch & RM=MFSCTRIB,Main      ,9153.6
555.3162
River Rch & RM=MFSCTRIB,Main      ,7754.1
563.1407
River Rch & RM=MFSCTRIB,Main      ,7317.8
718.8464
River Rch & RM=MFSCTRIB,Main      ,6404.1
765.5394
River Rch & RM=MFSCTRIB,Main      ,3748
842.5540
River Rch & RM=MFSCTRIB,Main      ,572.1
917.6873
River Rch & RM=MFSCTRIB,Main      ,172.1
922.7677
Boundary for River Rch & Prof#=MFSCTRIB,Main      ,1
Up Type=0
Dn Type=3
Dn Slope=0.013344

--- MFSCTRIB.g01 (geometry) ---

Geom Title=USGS 10m DEM
Program Version=4.10

River Reach=MFSCTRIB        ,Main
Reach XY= 30
     2323846.064       340408.06     2323340.856      340281.323
      2322901.62      340373.337     2322582.176      340557.365
     2322370.636       340816.55      2322455.44      340871.601
     2322458.912      340944.518     2322335.648       341081.67
     2322398.148      341437.573     2322162.943      341688.403
     2321849.537       341947.99     2321500.578      342071.254
     2321332.175      342435.837     2321149.629      342485.821
     2321132.962      342553.876     2320988.425      342637.226
     2320777.986      342672.688     2320739.039      342750.057
     2320649.803       342714.64     2320501.712       343054.05
     2320320.023      343060.837     2319860.393       343543.46
     2319665.509       343876.81     2319450.231      344015.698
     2319332.176       344229.24     2318903.969      344434.605
     2318826.967      344550.421     2318795.717      344883.754
     2318141.133      345364.315     2317648.114      345606.372

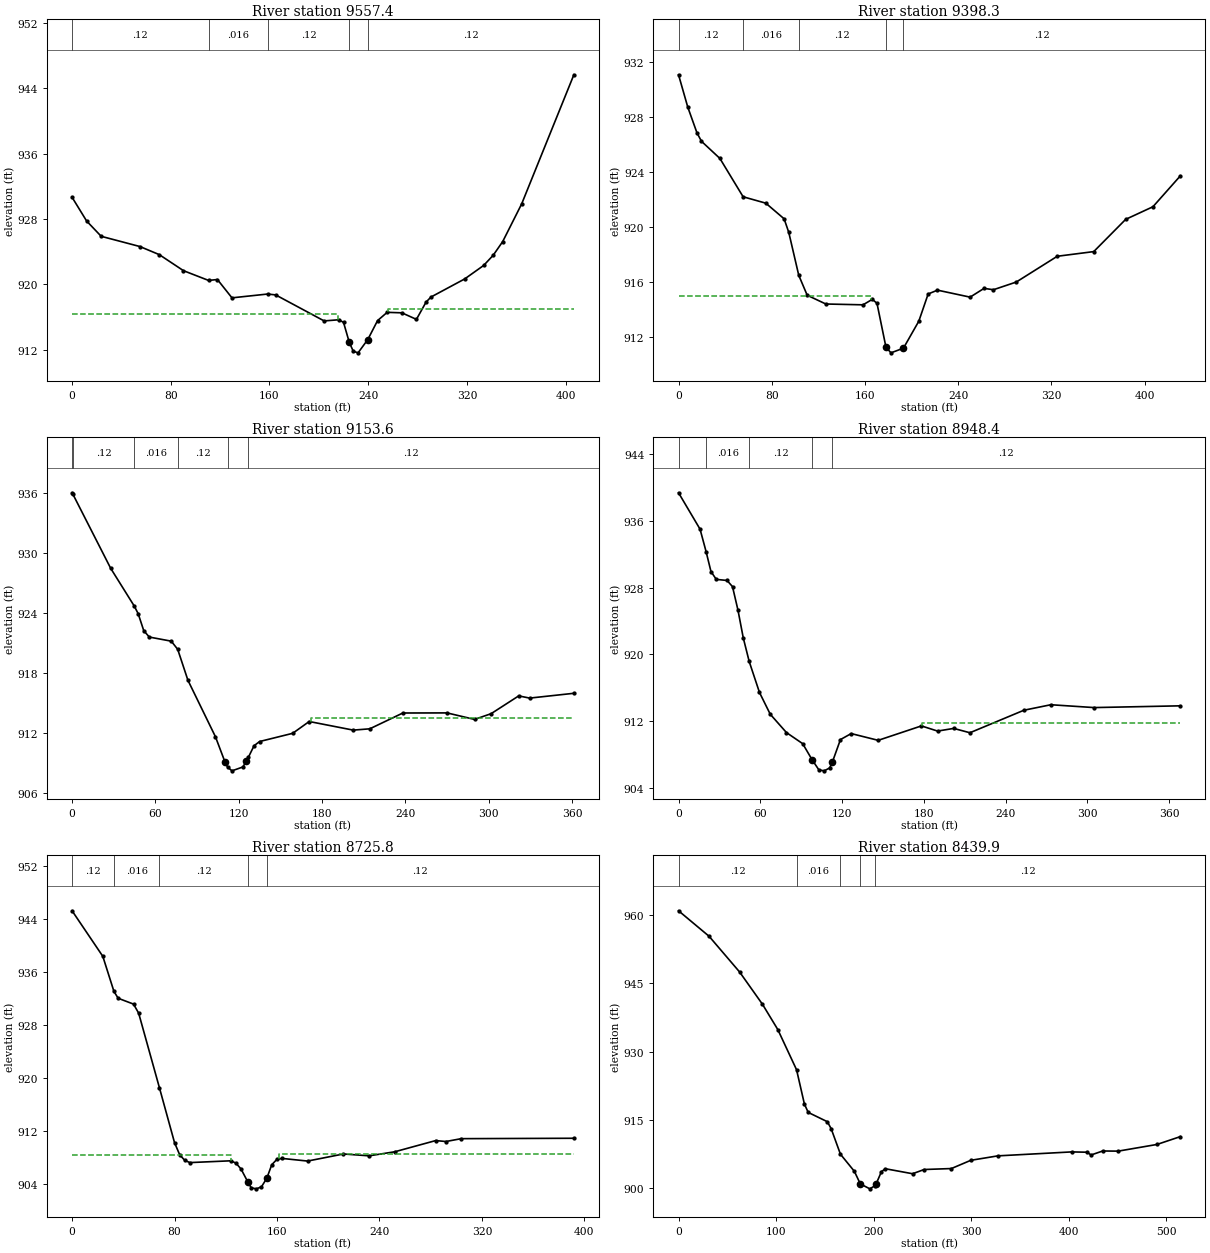
Type RM Length L Ch R = 1 ,9557.4  ,146,159,171.8
XS GIS Cut Line= 4
     2323785.483      340184.584     2323835.315      340341.831
     2323829.671      340487.306     2323852.757      340580.634
#Sta/Elev= 30
       0  930.65    11.8  927.75    23.6  925.88      55  924.63    70.7  923.64
    90.3  921.68  110.64 920.488   117.8   920.6   129.6  918.36  158.47918.8251
     165  918.72   204.3  915.54   216.1  915.68     220  915.37   224.7  912.91
   227.9  911.84   231.8  911.64   239.7  913.27   247.6  915.58   255.4  916.59
   267.3  916.53   279.1  915.73   286.9  917.84   290.9  918.46   318.2  920.67
   333.6  922.32   341.3  923.56     349  925.23   364.4  929.84   406.7  945.62
#Mann= 5 ,-1 , 0
       0     .12       0  110.64    .016       0  158.47     .12       0
   224.7    .045       0   239.7     .12       0
#XS Ineff= 2 , 0
          215.69  916.35  256.45          916.96
Permanent Ineff=
       F       F
Bank Sta=224.7,239.7
XS Rating Curve= 0 ,0
Exp/Cntr=0.3,0.1

Type RM Length L Ch R = 1 ,9398.3  ,256.6,244.7,232.3
XS GIS Cut Line= 4
     2323736.654      340195.434      2323739.91      340301.771
     2323641.168      340437.405     2323740.995      340557.848
#Sta/Elev= 30
       0   931.1     7.9  928.75    15.8  926.87    19.7  926.25    35.5     925
   55.42922.2065    74.9  921.74    90.6   920.6    94.6  919.61  103.16916.4829
   110.4  915.03   126.4  914.39   158.3  914.33   166.3  914.73   170.3  914.44
     178  911.24   182.3  910.83     193  911.17   206.2  913.14   214.2  915.12
   222.2   915.4   250.2  914.89   262.2  915.53   270.2  915.43   289.8  915.99
     325  917.87   356.3  918.21   383.7  920.56   407.1  921.48   430.6  923.73
#Mann= 5 ,-1 , 0
       0     .12       0   55.42    .016       0  103.16     .12       0
     178    .045       0     193     .12       0
#XS Ineff= 2 , 0
          165.12  914.98
Permanent Ineff=
       F       F
Bank Sta=178,193
XS Rating Curve= 0 ,0
Exp/Cntr=0.3,0.1

Type RM Length L Ch R = 1 ,9153.6  ,209.5,205.2,200.9
XS GIS Cut Line= 2
     2323480.578      340172.648     2323454.536      340532.891
#Sta/Elev= 30
       0  936.02     .53935.8942    27.8  928.47    44.8 924.691    47.6  923.93
    51.6  922.24    55.6   921.6    71.4  921.19   76.03920.3755    83.4  917.28
   103.2  911.64  110.06909.1187   111.9  908.61   115.1  908.23     123  908.62
  125.26909.1763   126.9  909.58     131  910.74     135  911.16   158.8  911.98
   170.7  913.16   202.4   912.3   214.3  912.43   238.1  914.01   269.9  914.02
   289.7  913.37   301.6  913.94   321.5  915.72   329.4   915.5   361.2  915.98
#Mann= 6 ,-1 , 0
       0     .08       0     .53     .12       0    44.8    .016       0
   76.03     .12       0   111.9    .045       0   126.9     .12       0
#XS Ineff= 2 , 0
                          171.72          913.51
Permanent Ineff=
       F       F
Bank Sta=110.06,125.26
XS Rating Curve= 0 ,0
Exp/Cntr=0.3,0.1

Type RM Length L Ch R = 1 ,8948.4  ,224.3,222.6,220.5
XS GIS Cut Line= 2
     2323255.969      340187.839     2323299.371      340553.507
#Sta/Elev= 30
       0  939.38    15.8  935.01   20.22932.3196    23.8  929.93    27.7  928.99
    35.6  928.86    39.6  928.12    43.6  925.31    47.5  921.97   51.85919.1389
    59.4  915.42    67.3  912.81    79.2  910.61    91.1  909.28    97.9  907.38
     103  906.13   106.9  906.02   110.9  906.37   112.9  907.08   118.8  909.77
   126.7  910.49   146.5  909.68   178.2  911.41   190.1  910.79   201.9  911.11
   213.8  910.59   253.4  913.29   273.2  913.95   304.9  913.61   368.2  913.82
#Mann= 5 ,-1 , 0
       0     .12       0   20.22    .016       0   51.85     .12       0
    97.9    .045       0   112.9     .12       0
#XS Ineff= 2 , 0
                          178.33          911.74
Permanent Ineff=
       F       F
Bank Sta=97.9,112.9
XS Rating Curve= 0 ,0
Exp/Cntr=0.3,0.1

Type RM Length L Ch R = 1 ,8725.8  ,292.9,285.9,278.6
XS GIS Cut Line= 2
      2323026.67      340212.162     2323106.229      340595.825
#Sta/Elev= 30
       0  945.29      24  938.42   32.69933.1244      36  932.09      48  931.21
      52  929.84   68.16918.6264      80  910.31      84  908.49      88  907.63
      92   907.3   123.9  907.57   127.9  907.23   131.9  906.34   137.1  904.43
   139.9  903.49   143.9  903.34   147.9  903.65   152.1  904.96   155.9  906.97
   159.9  907.78   163.9  907.93   183.9  907.53   211.9   908.6   231.9  908.32
   251.9  908.93   283.9  910.62   291.9  910.48   303.9  910.91   391.8  910.97
#Mann= 5 ,-1 , 0
       0     .12       0   32.69    .016       0   68.16     .12       0
   137.1    .045       0   152.1     .12       0
#XS Ineff= 2 , 0
          123.84  908.45   161.4          908.53
Permanent Ineff=
       F       F
Bank Sta=137.1,152.1
XS Rating Curve= 0 ,0
Exp/Cntr=0.3,0.1

Type RM Length L Ch R = 1 ,8439.9  ,402.1,393.2,376.2
XS GIS Cut Line= 3
     2322792.644      340246.433     2322779.623      340410.278
     2322949.979      340716.268
#Sta/Elev= 30
       0  960.98    31.3  955.38    62.6  947.53    86.1  940.42   101.8  934.87
  121.05926.0249   129.1  918.48     133  916.65   152.6  914.61   156.5  913.09
  166.05907.4592   180.3  903.71   186.4  900.94   196.2  899.85   201.4  900.54
  202.71900.9705   208.1  903.63   212.1  904.27     240  903.17   251.9   904.1
   279.8  904.31   299.7  906.12   327.5   907.1   403.2  907.97   419.1   907.9
     423  907.29     435  908.17   450.9  908.14   490.7  909.61   514.6  911.33
#Mann= 5 ,-1 , 0
       0     .12       0  121.05    .016       0  166.05     .12       0
   186.4    .045       0   201.4     .12       0
Bank Sta=186.4,202.71
XS Rating Curve= 0 ,0
Exp/Cntr=0.3,0.1

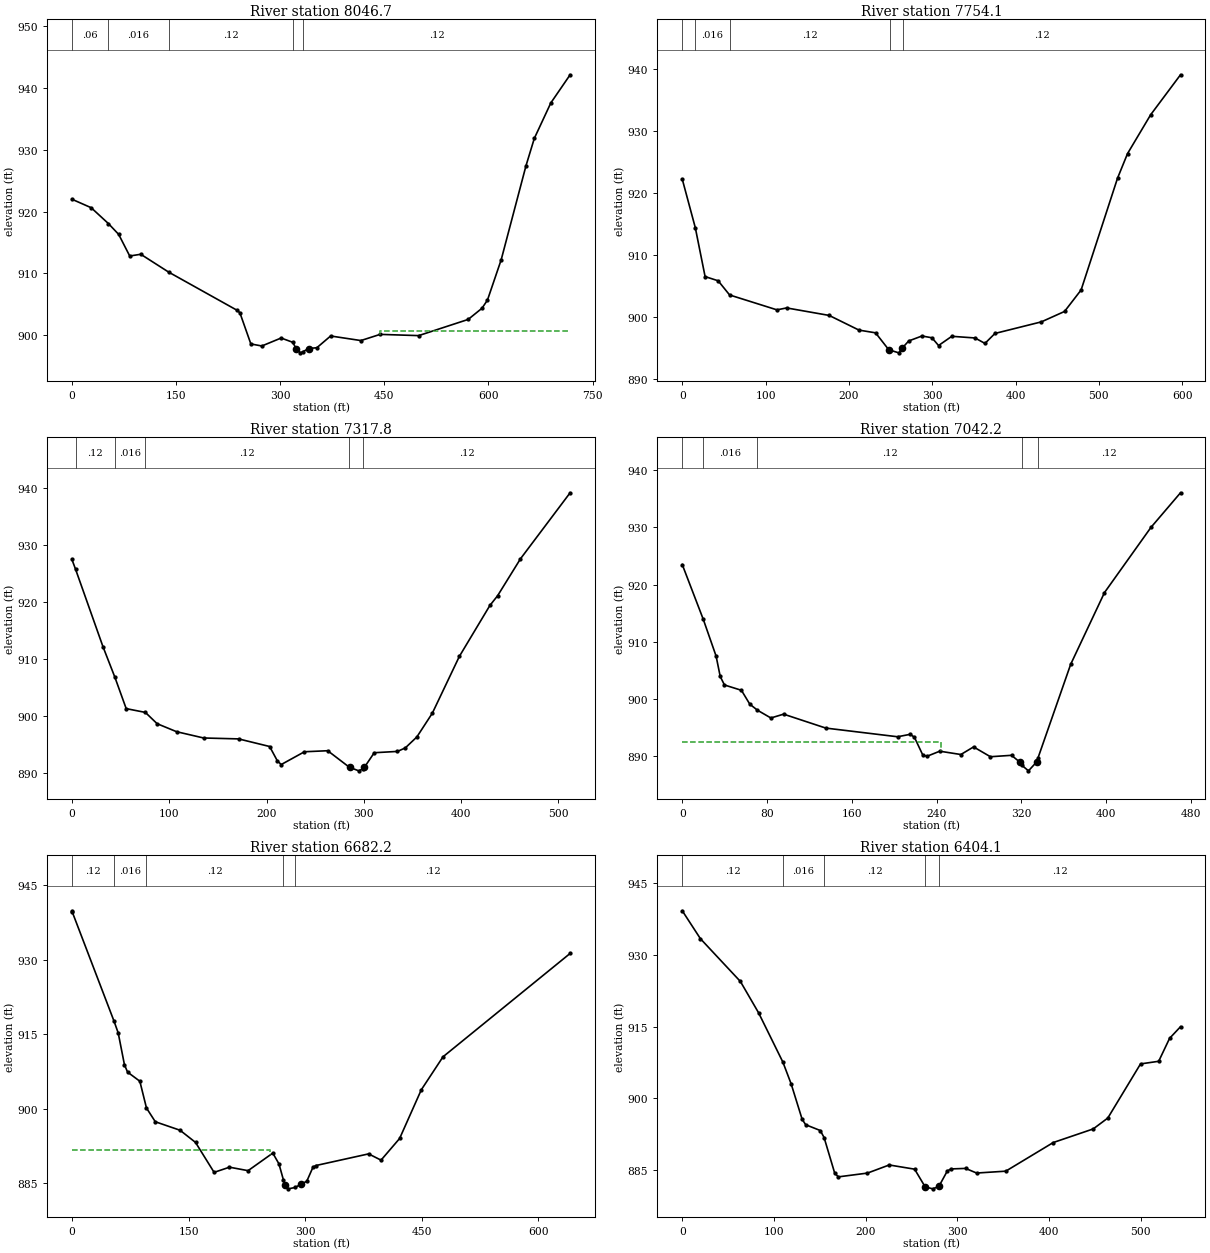
Type RM Length L Ch R = 1 ,8046.7  ,295.4,292.6,320.4
XS GIS Cut Line= 4
     2322194.771      340540.487     2322383.573      340565.443
     2322699.328      340762.926     2322779.623      340895.304
#Sta/Elev= 30
       0     922    27.8  920.62   52.55918.0579    67.4   916.3    83.3   912.8
    99.2  913.08   139.5910.1831     238     904     242   903.6   257.8  898.55
   273.6  898.22   301.4  899.51   318.1  898.82  323.17897.7663   329.1  897.11
   333.1  897.31     341  897.81   352.9  897.94   372.7  899.84   416.3   899.1
     444   900.1   499.5   899.9   570.8  902.52   590.7  904.33   598.6  905.65
   618.4  912.19   654.2  927.45   666.1  931.85   689.9   937.6   717.7  942.16
#Mann= 5 ,-1 , 0
       0     .06       0   52.55    .016       0   139.5     .12       0
   318.1    .045       0   333.1     .12       0
#XS Ineff= 2 , 0
                          443.34          900.64
Permanent Ineff=
       F       F
Bank Sta=323.17,341
XS Rating Curve= 0 ,0
Exp/Cntr=0.3,0.1

Type RM Length L Ch R = 1 ,7754.1  ,443,436.3,384.5
XS GIS Cut Line= 4
     2322153.538      340743.394     2322301.108       340832.37
     2322550.674      340856.242     2322692.818      340958.238
#Sta/Elev= 30
       0  922.27   15.64 914.448    27.4  906.55    43.1  905.87   56.79 903.584
   113.6  901.18   125.3  901.49   176.3  900.28   212.1  897.91     232  897.47
   247.9  894.73   249.4  894.67   259.9  894.24   263.8  894.97   264.4  895.07
   271.8  896.16   287.7  896.96   299.7  896.67   307.6  895.42   323.5  896.91
   351.4  896.64   363.3  895.76   375.3  897.37     431  899.24   458.8  900.92
   478.7  904.39   522.4  922.43   534.4   926.4   562.2  932.68     598  939.13
#Mann= 5 ,-1 , 0
       0     .12       0   15.64    .016       0   56.79     .12       0
   249.4    .045       0   264.4     .12       0
Bank Sta=247.9,263.8
XS Rating Curve= 0 ,0
Exp/Cntr=0.3,0.1

Type RM Length L Ch R = 1 ,7317.8  ,270.6,275.6,281.2
XS GIS Cut Line= 3
     2322087.349      341153.551     2322473.634      341162.231
     2322591.906      341204.549
#Sta/Elev= 30
       0  927.42    3.79925.6861    31.9  912.16    44.2 906.784    55.8   901.3
   75.51900.6371    87.6  898.66   107.6  897.26   135.4  896.16   171.3     896
   203.2  894.67   211.1  892.17   215.1  891.51     239  893.75   262.9  893.93
   284.5  891.12  285.68891.0071   294.8  890.41   299.5  890.81  300.52891.0108
   310.7  893.58   334.6  893.81   342.6  894.42   354.5  896.34   370.4   900.5
   398.2  910.45   429.6  919.37   437.4  921.04     461  927.53     512  939.08
#Mann= 5 ,-1 , 0
    3.79     .12       0    44.2    .016       0   75.51     .12       0
   284.5    .045       0   299.5     .12       0
Bank Sta=285.68,300.52
XS Rating Curve= 0 ,0
Exp/Cntr=0.3,0.1

Type RM Length L Ch R = 1 ,7042.2  ,348,360,371.4
XS GIS Cut Line= 2
     2322085.179      341339.098     2322537.653      341466.051
#Sta/Elev= 30
       0   923.5   19.87913.8831    31.9  907.48    35.8   903.9    39.8  902.41
    55.8  901.48    63.7  899.05   70.95897.9875    83.6  896.63    95.6   897.3
   135.4  894.86   203.1  893.34   215.1  893.77     219  893.24     227   890.1
     231  889.93   242.9  890.81   262.8  890.23   274.8  891.56   290.7  889.84
   310.6  890.09   318.6  888.87   320.5  888.32   326.6  887.37   334.5  888.97
   335.5  889.59   366.4  906.03   398.3   918.6   442.1  930.01     470  936.08
#Mann= 5 ,-1 , 0
       0     .12       0   19.87    .016       0   70.95     .12       0
   320.5    .045       0   335.5     .12       0
#XS Ineff= 2 , 0
          244.07  892.36
Permanent Ineff=
       F       F
Bank Sta=318.6,334.5
XS Rating Curve= 0 ,0
Exp/Cntr=0.3,0.1

Type RM Length L Ch R = 1 ,6682.2  ,274.1,278.1,281.4
XS GIS Cut Line= 3
     2321973.417      341480.157     2322232.748      341754.679
     2322482.314      341671.129
#Sta/Elev= 30
       0  939.83     .63939.5244   54.24917.5819    59.6  915.21    67.6  908.82
    71.6  907.34    87.4   905.5   95.92900.1068   107.3  897.34   139.1  895.63
     159  893.18   182.9  887.15   202.7  888.19   226.6  887.49   258.4  891.03
   266.3  888.86     272  885.66   274.3  884.52   278.3  883.83     287   884.1
   294.2  884.72   302.1  885.36   310.1   888.2     314  888.53   381.6  890.87
   397.6  889.61   421.5  893.97   449.4  903.78   477.3  910.42   640.8  931.24
#Mann= 5 ,-1 , 0
     .63     .12       0   54.24    .016       0   95.92     .12       0
     272    .045       0     287     .12       0
#XS Ineff= 2 , 0
          254.28  891.66
Permanent Ineff=
       F       F
Bank Sta=274.3,294.2
XS Rating Curve= 0 ,0
Exp/Cntr=0.3,0.1

Type RM Length L Ch R = 1 ,6404.1  ,304.5,302.9,298.4
XS GIS Cut Line= 4
     2321787.365      341613.903     2321943.328      341847.847
     2322019.932      341959.451     2322122.071      342034.627
#Sta/Elev= 30
       0  939.25    19.8   933.4    63.4  924.44    83.2  917.89  109.78 907.528
   118.8  902.96   130.7  895.59   134.6  894.43   150.5  893.22  154.67891.7507
   166.3  884.26   170.3  883.51     202   884.3   225.7     886   253.4  885.12
   264.9  881.41   273.2     881   279.9  881.52   289.1  884.75   293.1  885.17
     309  885.28     321  884.31   352.8   884.7   404.6   890.7   448.2  893.55
   464.1  895.83   499.8  907.17   519.6  907.72   531.5  912.53   543.4  914.96
#Mann= 5 ,-1 , 0
       0     .12       0  109.78    .016       0  154.67     .12       0
   264.9    .045       0   279.9     .12       0
Bank Sta=264.9,279.9
XS Rating Curve= 0 ,0
Exp/Cntr=0.3,0.1

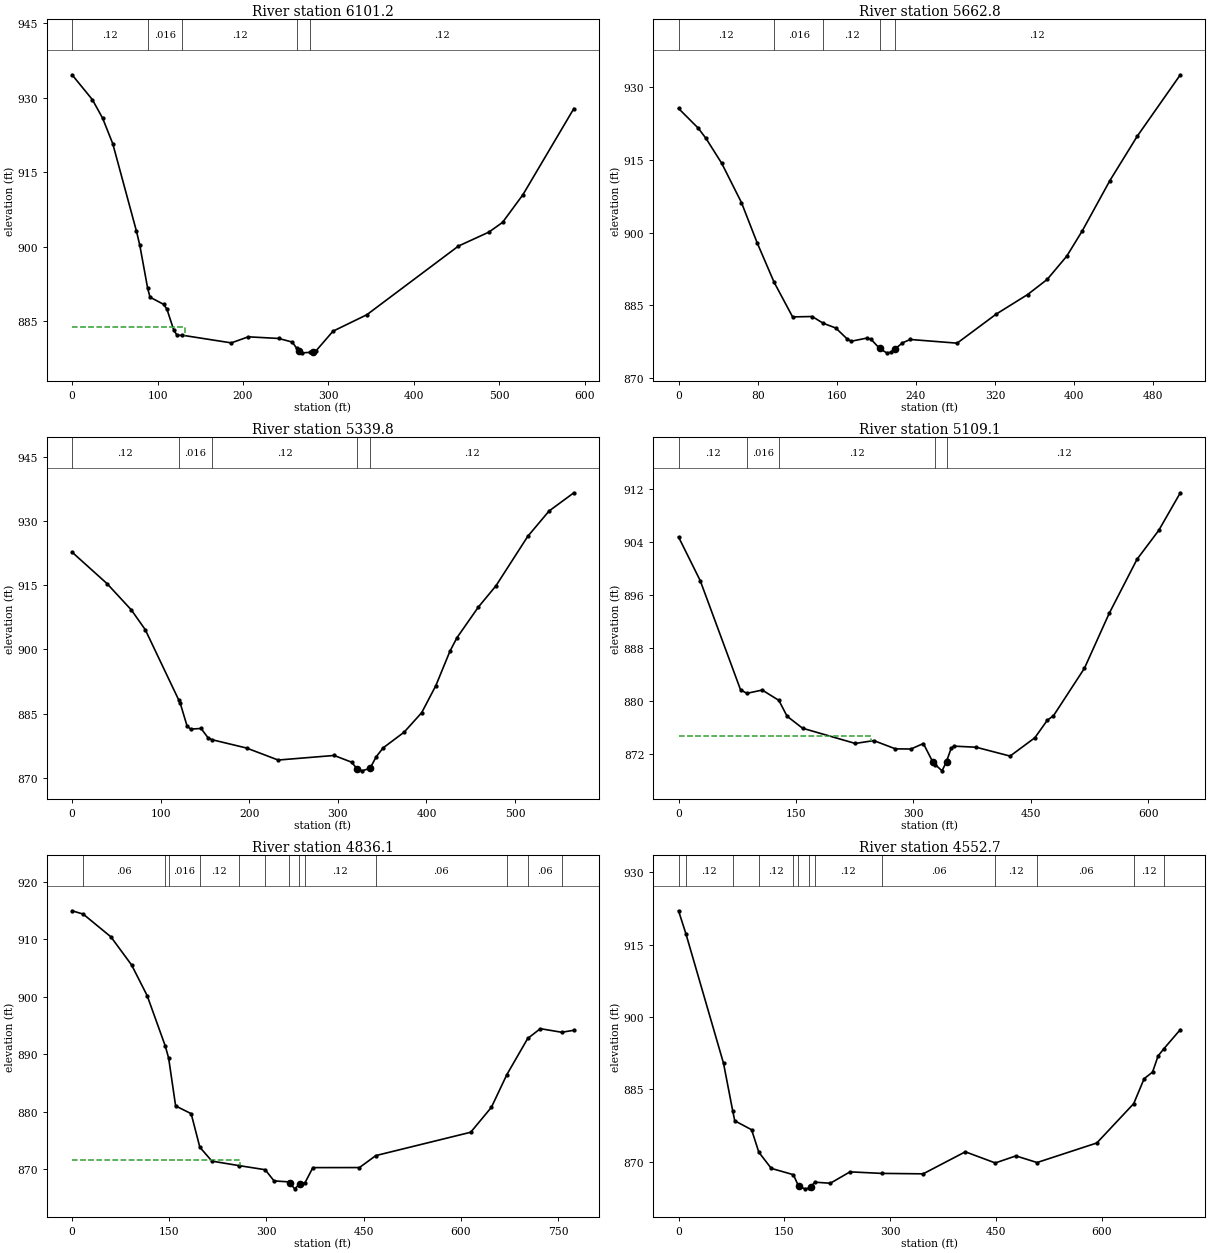
Type RM Length L Ch R = 1 ,6101.2  ,443.4,438.4,431.7
XS GIS Cut Line= 3
     2321544.055      341804.592     2321795.791      342116.007
     2321800.131      342302.639
#Sta/Elev= 30
       0  934.59    23.8  929.58    35.7  925.88    47.6  920.74    75.3  903.17
    79.3  900.27    88.4   891.7    91.2  889.88     107  888.45     111  887.47
   118.9  883.31   122.9  882.18  129.05882.2288   186.3  880.69   206.2  881.91
   241.8  881.58   257.7  880.85   262.8   879.6   265.6  878.97   269.6  878.69
   277.8  878.78   281.5  878.92   285.5  879.11   305.3  883.04   344.9  886.35
   452.1  900.16   487.8  902.97   503.7  904.92   527.5  910.48   587.1   927.8
#Mann= 5 ,-1 , 0
       0     .12       0    88.4    .016       0  129.05     .12       0
   262.8    .045       0   277.8     .12       0
#XS Ineff= 2 , 0
          132.51  883.95
Permanent Ineff=
       F       F
Bank Sta=265.6,281.5
XS Rating Curve= 0 ,0
Exp/Cntr=0.3,0.1

Type RM Length L Ch R = 1 ,5662.8  ,312.8,322.9,332.5
XS GIS Cut Line= 3
     2321287.978      342094.306     2321370.444      342196.302
     2321677.518      342413.316
#Sta/Elev= 30
       0  925.52    19.9  921.47    27.8  919.34    43.7  914.22    63.6  906.16
    79.5  897.87   96.59889.7794   115.3  882.65   135.1  882.73  146.28881.3358
   158.9  880.37   170.7  878.07   174.7  877.65   190.5   878.3   194.5  878.06
   203.3  876.16   210.3  875.26   214.3  875.36   218.3  875.96   226.2  877.29
   234.1  878.01   281.6  877.25   321.2  883.24   352.8  887.24   372.6  890.35
   392.4  895.14   408.2  900.38   435.9  910.65   463.6  919.79   507.2  932.44
#Mann= 5 ,-1 , 0
       0     .12       0   96.59    .016       0  146.28     .12       0
   203.3    .045       0   218.3     .12       0
Bank Sta=203.3,218.3
XS Rating Curve= 0 ,0
Exp/Cntr=0.3,0.1

Type RM Length L Ch R = 1 ,5339.8  ,227.6,230.7,228
XS GIS Cut Line= 4
     2321137.154      342173.516     2321150.174      342314.575
     2321278.213      342532.674     2321433.378      342606.459
#Sta/Elev= 30
       0  922.79    39.4  915.43    66.9  909.26    82.6  904.64  120.34888.1979
     122  887.48   129.8  882.08   133.8  881.35   145.6   881.5   153.5  879.32
  158.17878.8591     197  876.92   232.6  874.11   295.8  875.18   315.5  873.61
   321.4  872.12   327.4  871.58   336.4  872.19   343.2  874.84   351.1  876.95
   374.8  880.63   394.6  885.19   410.6  891.53   426.5  899.58   434.5  902.77
   458.5   909.9   478.5  914.92   514.4   926.5   538.4  932.42   566.4  936.69
#Mann= 5 ,-1 , 0
       0     .12       0  120.34    .016       0  158.17     .12       0
   321.4    .045       0   336.4     .12       0
Bank Sta=321.4,336.4
XS Rating Curve= 0 ,0
Exp/Cntr=0.3,0.1

Type RM Length L Ch R = 1 ,5109.1  ,271.6,273,272.8
XS GIS Cut Line= 4
     2321030.998      342248.928     2321009.296      342413.859
     2321152.525      342691.637     2321304.435       342748.06
#Sta/Elev= 30
       0  904.81    27.7  898.21    79.2  881.71   87.22881.1757   106.9  881.67
  128.15880.1091   138.6  877.72   158.4   875.9   225.7   873.6   249.4  874.03
   277.1  872.78   296.9  872.76   312.7  873.59   324.6  870.83   328.1  870.38
   336.5  869.46  342.37870.8599   343.1  871.16   348.3   872.9   352.3  873.19
     380  873.03   423.5  871.69   455.2  874.47     471  877.11   478.9  877.79
   518.4  884.96     550  893.25   585.6  901.44   613.3   905.8   640.9  911.49
#Mann= 5 ,-1 , 0
       0     .12       0   87.22    .016       0  128.15     .12       0
   328.1    .045       0   343.1     .12       0
#XS Ineff= 2 , 0
          246.34   874.8
Permanent Ineff=
       F       F
Bank Sta=324.6,342.37
XS Rating Curve= 0 ,0
Exp/Cntr=0.3,0.1

Type RM Length L Ch R = 1 ,4836.1  ,284.2,283.5,270.7
XS GIS Cut Line= 3
     2320703.126      342362.318     2320964.628      342901.598
     2321139.324      342912.448
#Sta/Elev= 30
       0  914.94   17.16914.3633    59.9  910.41    91.9  905.51   115.9  900.18
  143.87891.4132  149.05889.3162   159.8  881.01   183.8  879.66  197.14873.8351
   215.8  871.41  257.07870.6381  298.03869.9141   311.7  867.97   334.6   867.8
   335.6  867.64   343.6  866.59   349.6  867.25   351.6  867.51  359.53867.6593
   371.6  870.28   443.5  870.29  468.76872.3723   615.2  876.43   647.1  880.76
  671.08886.4705   703.2892.7433   722.7  894.44  755.69893.8151   774.4  894.16
#Mann= 13 ,-1 , 0
   17.16     .06       0  143.87     .12       0  149.05    .016       0
  197.14     .12       0  257.07     .06       0  298.03     .12       0
   334.6    .045       0   349.6     .06       0  359.53     .12       0
  468.76     .06       0  671.08     .12       0   703.2     .06       0
  755.69     .12       0
#XS Ineff= 2 , 0
          258.41  871.66
Permanent Ineff=
       F       F
Bank Sta=335.6,351.6
XS Rating Curve= 0 ,0
Exp/Cntr=0.3,0.1

Type RM Length L Ch R = 1 ,4552.7  ,241.4,231,211.1
XS GIS Cut Line= 3
     2320531.866       342591.81     2320846.536      342978.095
     2320831.345      343190.769
#Sta/Elev= 30
       0  922.02   10.57917.1985    63.8  890.38   76.83880.5149    79.7  878.47
   103.6  876.61  113.83871.9508   131.5   868.6  162.82867.2915   169.5  865.13
  170.48864.8618   179.4  864.36   184.5  864.48   187.3   864.8  193.32865.7382
   215.2  865.52   243.1  867.88  287.93867.5646   346.8  867.47   406.6  872.04
  449.06869.7267   478.3  871.19  508.28869.8145     593  873.87   645.3  882.03
   660.1   887.2     672  888.57   679.9  891.92  688.09893.4178   711.4  897.38
#Mann= 13 ,-1 , 0
       0     .06       0   10.57     .12       0   76.83    .016       0
  113.83     .12       0  162.82     .06       0   169.5    .045       0
   184.5     .06       0  193.32     .12       0  287.93     .06       0
  449.06     .12       0  508.28     .06       0   645.3     .12       0
  688.09     .06       0
Bank Sta=170.48,187.3
XS Rating Curve= 0 ,0
Exp/Cntr=0.3,0.1

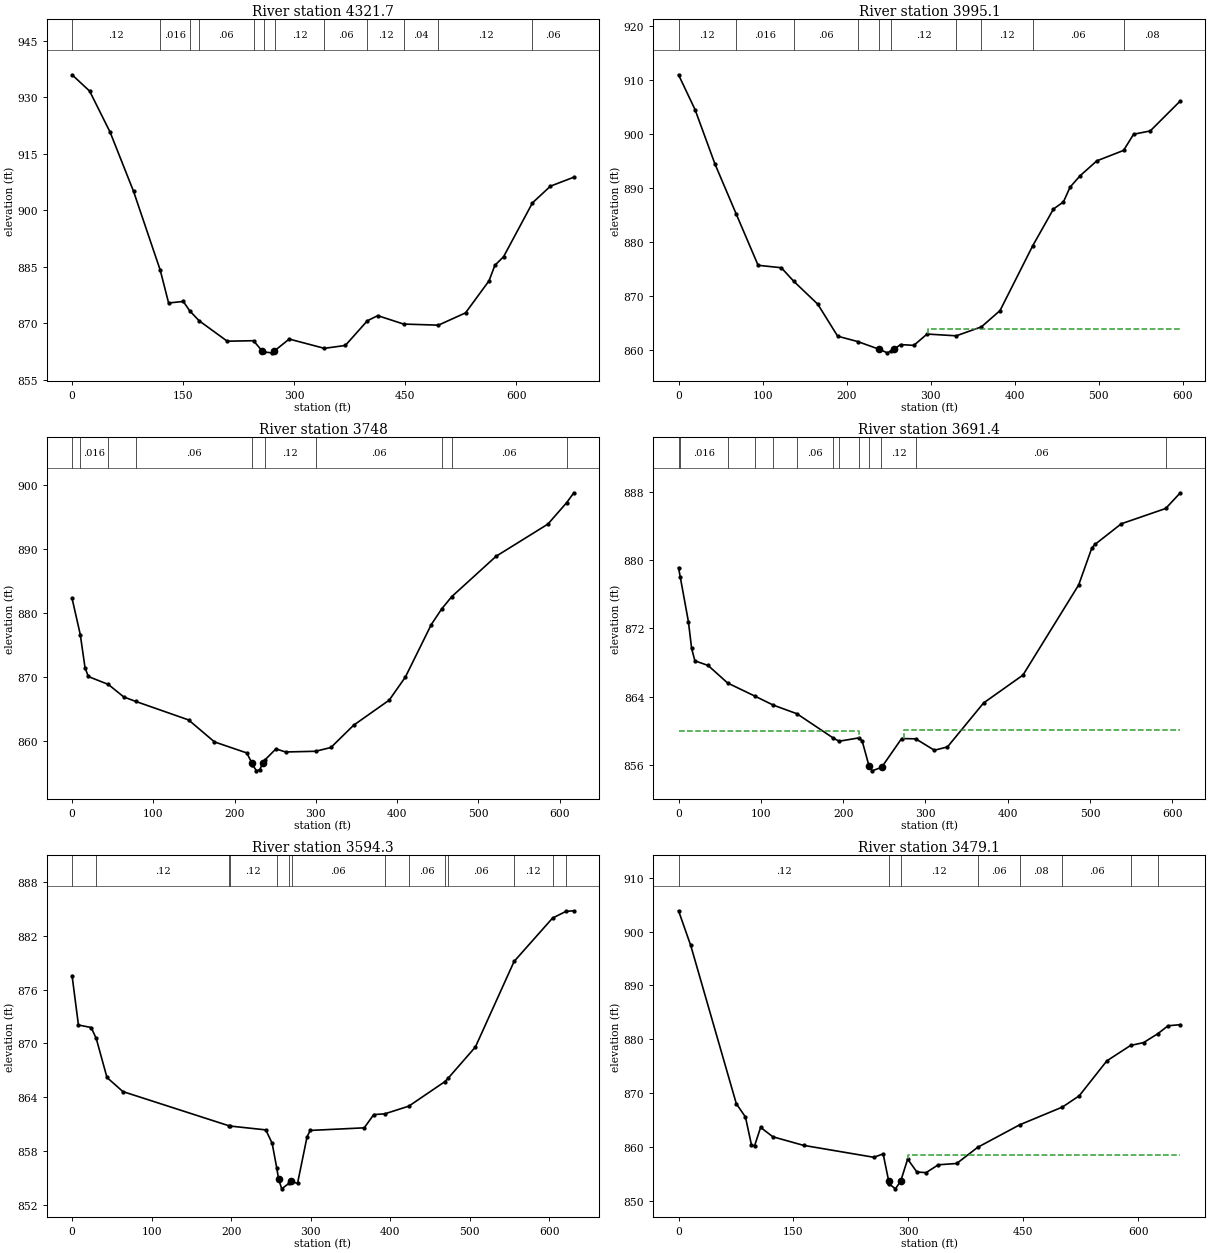
Type RM Length L Ch R = 1 ,4321.7  ,308.7,326.6,341.5
XS GIS Cut Line= 4
     2320338.543      342732.327     2320473.091      342860.365
     2320673.829      342966.702     2320683.595      343231.459
#Sta/Elev= 30
       0  935.99    23.7  931.66    51.4  920.74      83  905.05  119.16884.0471
   130.4  875.38   150.2  875.79  159.01873.2744  171.62870.6633   209.6  865.23
  245.09865.3638  256.69862.6364   259.2  862.38   269.4  862.14   273.4  862.57
   274.2  862.79   293.3   865.8  340.81863.3351   369.1   864.1  398.88870.6601
   412.9  872.02  447.79869.7818  494.86869.4913   531.5  872.76   563.2  881.26
   571.1  885.38   582.9  887.68  621.91901.9796   646.2  906.41   677.8  908.79
#Mann= 12 ,-1 , 0
       0     .12       0  119.16    .016       0  159.01     .12       0
  171.62     .06       0  245.09     .12       0   259.2    .045       0
   274.2     .12       0  340.81     .06       0  398.88     .12       0
  447.79     .04       0  494.86     .12       0  621.91     .06       0
Bank Sta=256.69,273.4
XS Rating Curve= 0 ,0
Exp/Cntr=0.3,0.1

Type RM Length L Ch R = 1 ,3995.1  ,250.4,247.1,243.7
XS GIS Cut Line= 4
     2320290.799      342806.112     2320315.756      342969.957
     2320417.753      343152.249     2320610.895      343262.926
#Sta/Elev= 30
       0  910.94    19.7  904.47    43.4   894.4    68.5885.2115    94.7  875.66
   122.3  875.21  137.17 872.695   165.7  868.46   189.4  862.53  213.07861.5463
   238.3  860.14   248.5  859.45   253.3  859.84   256.4  860.12   264.3  860.98
     280  860.83   295.8  862.93  330.55862.6013   360.5864.2615   382.6  867.27
  421.59879.2925   446.2  886.08   458.1   887.4     466  890.14     478  892.25
   497.8     895  529.66896.9338   541.6  899.93   561.4  900.54   597.2   906.1
#Mann= 10 ,-1 , 0
       0     .12       0    68.5    .016       0  137.17     .06       0
  213.07     .12       0   238.3    .045       0   253.3     .12       0
  330.55     .06       0   360.5     .12       0  421.59     .06       0
  529.66     .08       0
#XS Ineff= 2 , 0
                          297.21          863.83
Permanent Ineff=
       F       F
Bank Sta=238.3,256.4
XS Rating Curve= 0 ,0
Exp/Cntr=0.3,0.1

Type RM Length L Ch R = 1 ,3748    ,55.7,56.5,57.4
XS GIS Cut Line= 3
     2320055.014      343028.551     2320279.623      343312.839
     2320502.062      343437.622
#Sta/Elev= 30
       0  882.27   10.12876.6088    15.9  871.49    19.9  870.09   44.66868.8461
    63.7  866.89   78.35866.2012   143.3  863.32   175.2  859.89     215  858.17
  221.19856.6072   221.9  856.36   226.9  855.38   230.9  855.56   234.9  856.61
   236.9  857.03   250.8   858.8   262.8  858.32   299.6858.4301   318.5  859.02
   346.4  862.49   390.2   866.4   410.1     870     442  878.19  454.65880.5994
  467.08882.5293   521.7  888.83   585.5  893.85  608.41 897.169   617.4  898.73
#Mann= 10 ,-1 , 0
       0     .12       0   10.12    .016       0   44.66     .12       0
   78.35     .06       0   221.9    .045       0   236.9     .12       0
   299.6     .06       0  454.65     .08       0  467.08     .06       0
  608.41    .016       0
Bank Sta=221.19,234.9
XS Rating Curve= 0 ,0
Exp/Cntr=0.3,0.1

Type RM Length L Ch R = 1 ,3691.4  ,99.3,97.2,95.1
XS GIS Cut Line= 2
     2320020.292      343058.933      2320379.45      343551.554
#Sta/Elev= 30
       0   879.1    2.02878.0344      12  872.77    15.9  869.63    19.9  868.18
    35.9  867.64   59.64865.5848   92.51864.0613  115.26862.9895  143.78861.9877
  187.46859.1716  195.06858.7675  219.19859.1597   223.1  858.79   231.4  855.88
   235.1   855.3   246.4   855.7     247  855.75     271  859.08  288.19859.0484
   310.8  857.71   326.7   858.1   370.6  863.25   418.4  866.51   486.1  877.07
   502.1   881.4     506  881.82   537.9  884.23  591.81886.0199   609.6  887.86
#Mann= 13 ,-1 , 0
       0     .12       0    2.02    .016       0   59.64     .12       0
   92.51     .06       0  115.26     .12       0  143.78     .06       0
  187.46     .12       0  195.06     .06       0  219.19     .12       0
   231.4    .045       0   246.4     .12       0  288.19     .06       0
  591.81    .016       0
#XS Ineff= 2 , 0
          218.89  859.91  273.79          860.08
Permanent Ineff=
       F       F
Bank Sta=231.4,247
XS Rating Curve= 0 ,0
Exp/Cntr=0.3,0.1

Type RM Length L Ch R = 1 ,3594.3  ,117.5,115.2,112.7
XS GIS Cut Line= 2
     2319916.125      343122.952     2320336.047      343593.872
#Sta/Elev= 30
       0  877.55       8  872.05      24  871.77    30.4 870.546    43.9   866.2
    63.9  864.63  197.45860.8119  198.12860.7935   243.6  860.36   251.6  858.87
   257.5  856.06   259.6  854.93   263.6  853.79   272.5  854.39   275.5  854.67
  276.07854.6172   283.5  854.39   295.5  859.59   299.5   860.3   367.4  860.59
   379.4  862.07     393862.1433  423.44863.0052  468.64865.7288  472.75866.1027
   507.2   869.6  555.87879.1359  604.23883.9684  621.17884.7154     631  884.78
#Mann= 14 ,-1 , 0
       0    .016       0    30.4     .12       0  197.45     .08       0
  198.12     .12       0   257.5    .045       0   272.5     .12       0
  276.07     .06       0     393     .08       0  423.44     .06       0
  468.64    .016       0  472.75     .06       0  555.87     .12       0
  604.23     .08       0  621.17    .016       0
Bank Sta=259.6,275.5
XS Rating Curve= 0 ,0
Exp/Cntr=0.3,0.1

Type RM Length L Ch R = 1 ,3479.1  ,206.1,205.3,204
XS GIS Cut Line= 3
     2319783.746      343304.158     2319894.424      343294.393
     2320294.814      343662.231
#Sta/Elev= 30
       0  903.88    15.9  897.44    75.4  868.03    87.3  865.56    95.2  860.35
    99.2   860.2   107.1  863.63   123.1  861.88   163.1  860.29     255  858.07
     267  858.71  274.28 853.626   274.9  853.13     283  852.21   289.9  853.64
     299  857.74     311  855.34     323  855.22     339  856.68     363  856.92
   390.3859.9195  444.94 864.093  501.01867.4113   522.9   869.5   558.9  875.99
  589.82878.8504   606.8  879.38  625.39881.0331   638.8  882.51   654.8  882.72
#Mann= 8 ,-1 , 0
       0     .12       0   274.9    .045       0   289.9     .12       0
   390.3     .06       0  444.94     .08       0  501.01     .06       0
  589.82     .08       0  625.39    .016       0
#XS Ineff= 2 , 0
                          299.07          858.41
Permanent Ineff=
       F       F
Bank Sta=274.28,289.9
XS Rating Curve= 0 ,0
Exp/Cntr=0.3,0.1

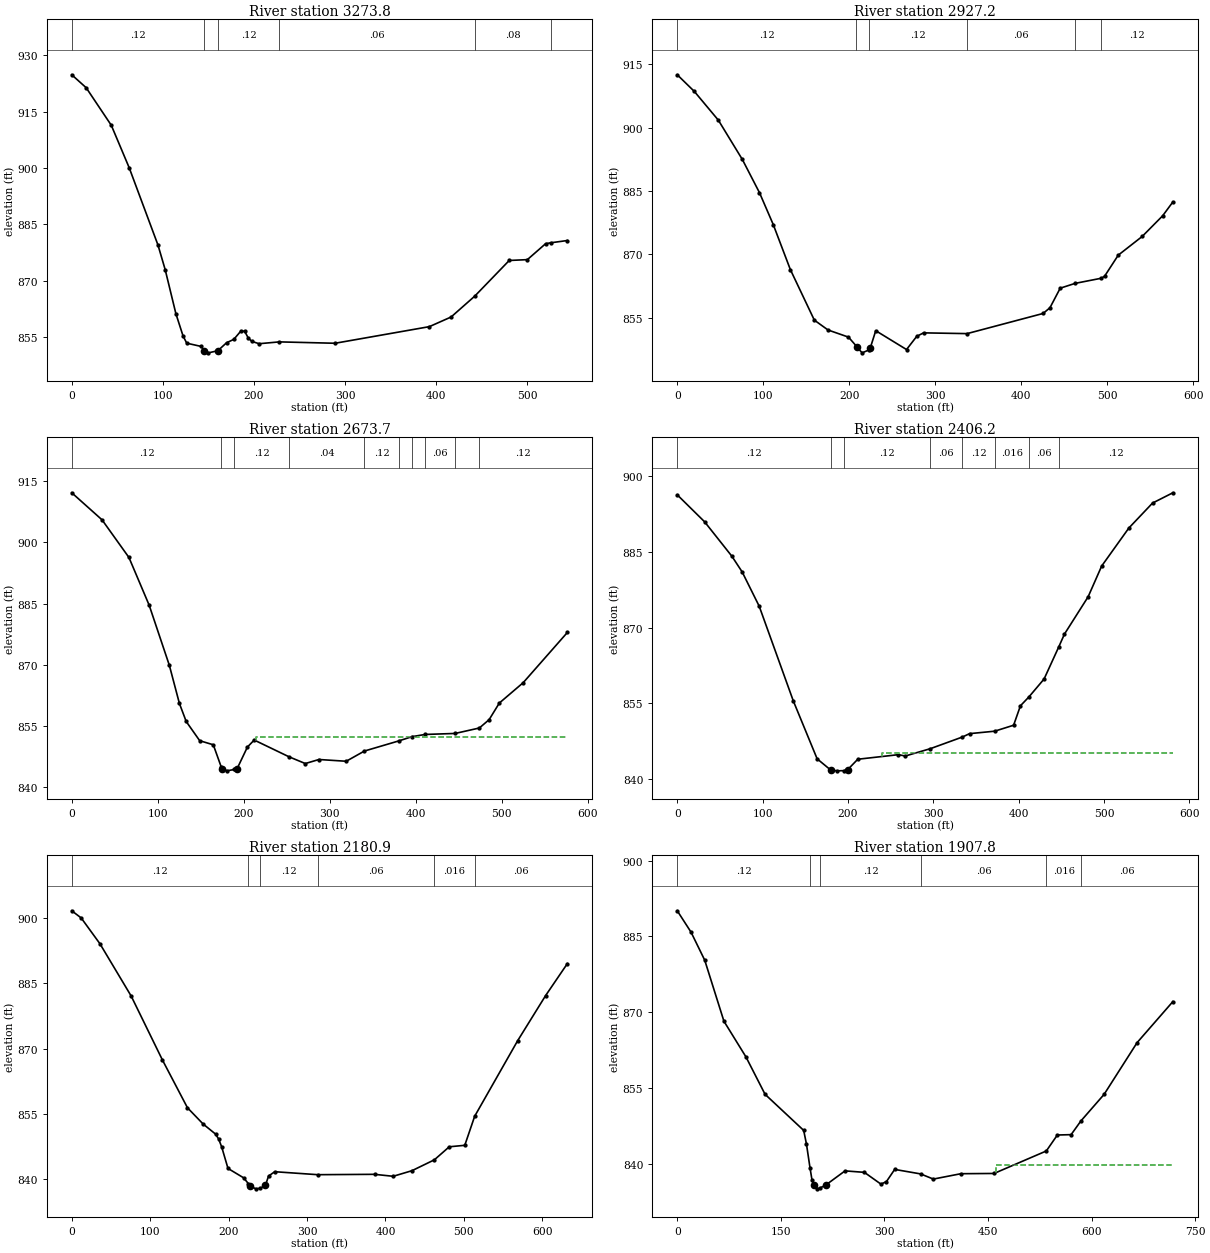
Type RM Length L Ch R = 1 ,3273.8  ,351.4,346.5,340.7
XS GIS Cut Line= 4
     2319723.308      343489.705      2319835.07      343513.577
     2320026.043      343675.252     2320190.973      343745.782
#Sta/Elev= 30
       0   924.8    15.8  921.36    43.4  911.35      63  900.07    94.6  879.49
   102.5  872.95   114.3  861.18   122.2  855.23   126.2  853.35   142.1  852.48
   145.3  851.38     150  850.78   160.3  851.34   169.9  853.47   177.8  854.36
   185.8  856.64   189.8   856.5   193.7  854.72   197.7  853.82   205.6  853.21
  227.81853.6966     289  853.33   392.4  857.75   416.3  860.32  442.32865.8876
   480.1  875.37     500  875.59     520  879.83  525.72880.0786   543.9  880.68
#Mann= 6 ,-1 , 0
       0     .12       0   145.3    .045       0   160.3     .12       0
  227.81     .06       0  442.32     .08       0  525.72    .016       0
Bank Sta=145.3,160.3
XS Rating Curve= 0 ,0
Exp/Cntr=0.3,0.1

Type RM Length L Ch R = 1 ,2927.2  ,244.2,253.6,263
XS GIS Cut Line= 3
     2319589.845      343655.721     2319644.098      343809.801
     2320013.022      343995.348
#Sta/Elev= 30
       0  912.53    19.9  908.58    47.8  901.78    75.7  892.48    95.6  884.63
   111.6  877.09   131.5  866.43   159.4  854.46   175.3  852.13   199.1  850.44
   208.4  848.28  209.15848.0262     215  846.72   223.4  847.45  224.61847.9789
   230.8  851.96   266.6   847.5   278.5  850.63   286.4  851.45  337.03 851.268
   425.4  856.04   433.4   857.4   445.3  862.02  462.55863.1554  493.02864.3747
   496.9  864.85   512.8  869.84   540.6  874.26   564.4  879.15   576.3  882.43
#Mann= 6 ,-1 , 0
       0     .12       0   208.4    .045       0   223.4     .12       0
  337.03     .06       0  462.55    .016       0  493.02     .12       0
Bank Sta=209.15,224.61
XS Rating Curve= 0 ,0
Exp/Cntr=0.3,0.1

Type RM Length L Ch R = 1 ,2673.7  ,266.9,267.5,267.6
XS GIS Cut Line= 4
     2319341.364       343878.16     2319467.232      343949.775
     2319607.206      344116.875     2319790.582      344226.467
#Sta/Elev= 30
       0  912.18    35.2  905.55    66.5  896.32      90  884.63   113.5  869.87
   125.2  860.52   133.1   856.1   148.8  851.39   164.6  850.39   173.9  844.91
  175.22844.5698   180.5     844   188.9  844.33   192.4  844.57   204.3  849.84
   212.2  851.55  252.63847.4487   271.6  845.79   287.5  846.78   319.2  846.35
  340.39848.8569  380.16851.3275  395.76852.3852  411.12852.9232  445.86853.1669
  474.02854.5029   485.4  856.55   497.3  860.63     525  865.61   576.4  877.93
#Mann= 10 ,-1 , 0
       0     .12       0   173.9    .045       0   188.9     .12       0
  252.63     .04       0  340.39     .12       0  380.16     .08       0
  395.76     .12       0  411.12     .06       0  445.86    .016       0
  474.02     .12       0
#XS Ineff= 2 , 0
                          214.24           852.3
Permanent Ineff=
       F       F
Bank Sta=175.22,192.4
XS Rating Curve= 0 ,0
Exp/Cntr=0.3,0.1

Type RM Length L Ch R = 1 ,2406.2  ,218,225.2,232.7
XS GIS Cut Line= 3
      2319278.43      344031.155     2319334.853      344176.554
     2319605.036      344504.245
#Sta/Elev= 30
       0  896.34      32     891      64  884.16      76  881.06      96  874.25
     136  855.44   163.9  843.96   179.8  841.74   180.4  841.72   187.7  841.58
   195.4  841.62   199.6   841.8   211.5  843.88   259.2  844.79   267.1  844.52
  296.39845.9696  334.13 848.293   342.5  848.96  371.88849.4446   394.1  850.63
   402.1  854.49  411.99 856.238   429.8   859.8  447.02866.1752   453.7  868.72
   481.4  876.11   497.3  882.22   529.1  889.75   556.9  894.71   580.7  896.75
#Mann= 8 ,-1 , 0
       0     .12       0   180.4    .045       0   195.4     .12       0
  296.39     .06       0  334.13     .12       0  371.88    .016       0
  411.99     .06       0  447.02     .12       0
#XS Ineff= 2 , 0
                          239.63          845.17
Permanent Ineff=
       F       F
Bank Sta=179.8,199.6
XS Rating Curve= 0 ,0
Exp/Cntr=0.3,0.1

Type RM Length L Ch R = 1 ,2180.9  ,277.5,273.1,268.7
XS GIS Cut Line= 4
     2319026.694      344139.662     2319142.796      344254.679
     2319248.048      344533.542     2319397.787      344614.922
#Sta/Elev= 30
       0  901.66      12  900.02    35.9   894.1    75.7  882.11   115.6  867.42
   147.5  856.46   167.4  852.74   183.3  850.42   187.3  849.28   191.2  847.44
   199.2  842.53   219.1  840.38   225.2  839.04     227  838.47     235  837.85
   240.2  837.98   246.9  838.63   250.9  840.78   258.8  841.78  313.61841.0977
     386  841.18   409.8  840.73   433.7  842.01  462.34844.5117   481.3   847.5
   501.1  847.84  513.72854.5082   568.5  871.84   604.2  882.21   631.9  889.54
#Mann= 6 ,-1 , 0
       0     .12       0   225.2    .045       0   240.2     .12       0
  313.61     .06       0  462.34    .016       0  513.72     .06       0
Bank Sta=227,246.9
XS Rating Curve= 0 ,0
Exp/Cntr=0.3,0.1

Type RM Length L Ch R = 1 ,1907.8  ,336.4,316.9,296.2
XS GIS Cut Line= 4
     2318900.355      344234.171     2318887.334       344368.72
     2319084.817       344683.39      2319290.98      344728.963
#Sta/Elev= 30
       0  890.08    19.9  885.87    39.8  880.31    67.6  868.25    99.4  861.22
   127.2   853.8   183.1  846.67   187.1     844   192.4  839.16   195.1  836.91
  197.69 835.887   203.1  835.12   207.4  835.33   215.1  835.87     243  838.67
     271  838.38     295  836.05     303  836.56   314.9  838.96  352.42838.0706
   370.9  837.05   410.8  838.11   458.8  838.16  534.52842.6038   550.5  845.76
   570.4  845.83  584.64848.5412   618.2  853.79     666  864.02   717.8  872.13
#Mann= 6 ,-1 , 0
       0     .12       0   192.4    .045       0   207.4     .12       0
  352.42     .06       0  534.52    .016       0  584.64     .06       0
#XS Ineff= 2 , 0
                          461.51          839.93
Permanent Ineff=
       F       F
Bank Sta=197.69,215.1
XS Rating Curve= 0 ,0
Exp/Cntr=0.3,0.1