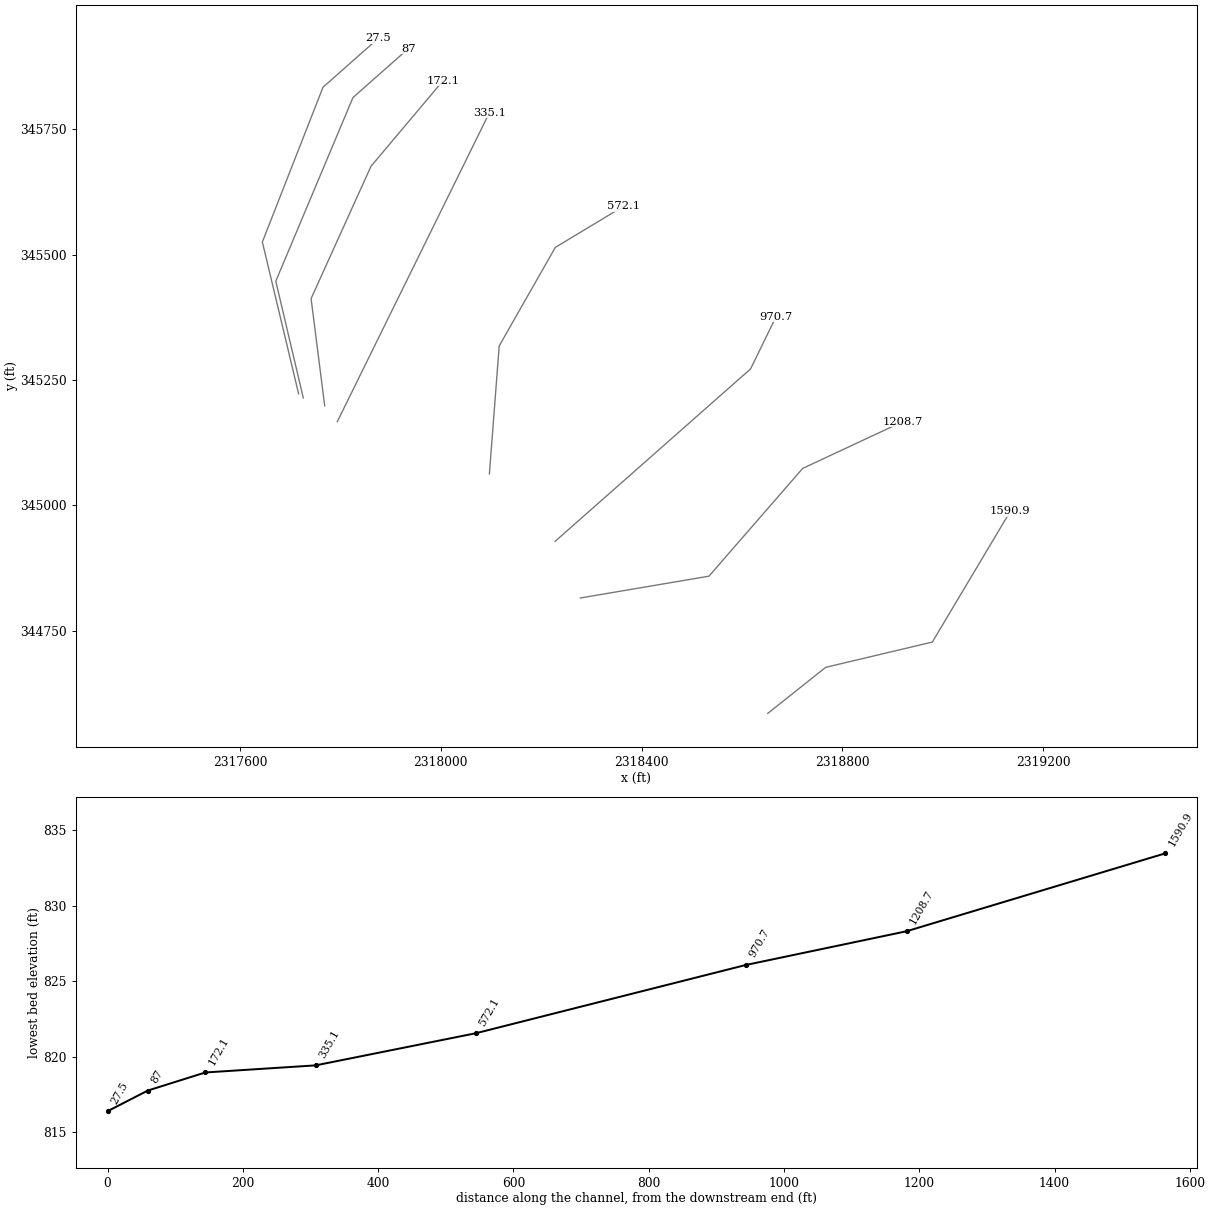
HEC-RAS study MFSCTRIB.prj: MFSCTRIB

--- MFSCTRIB.g01 (geometry) --- (continued)

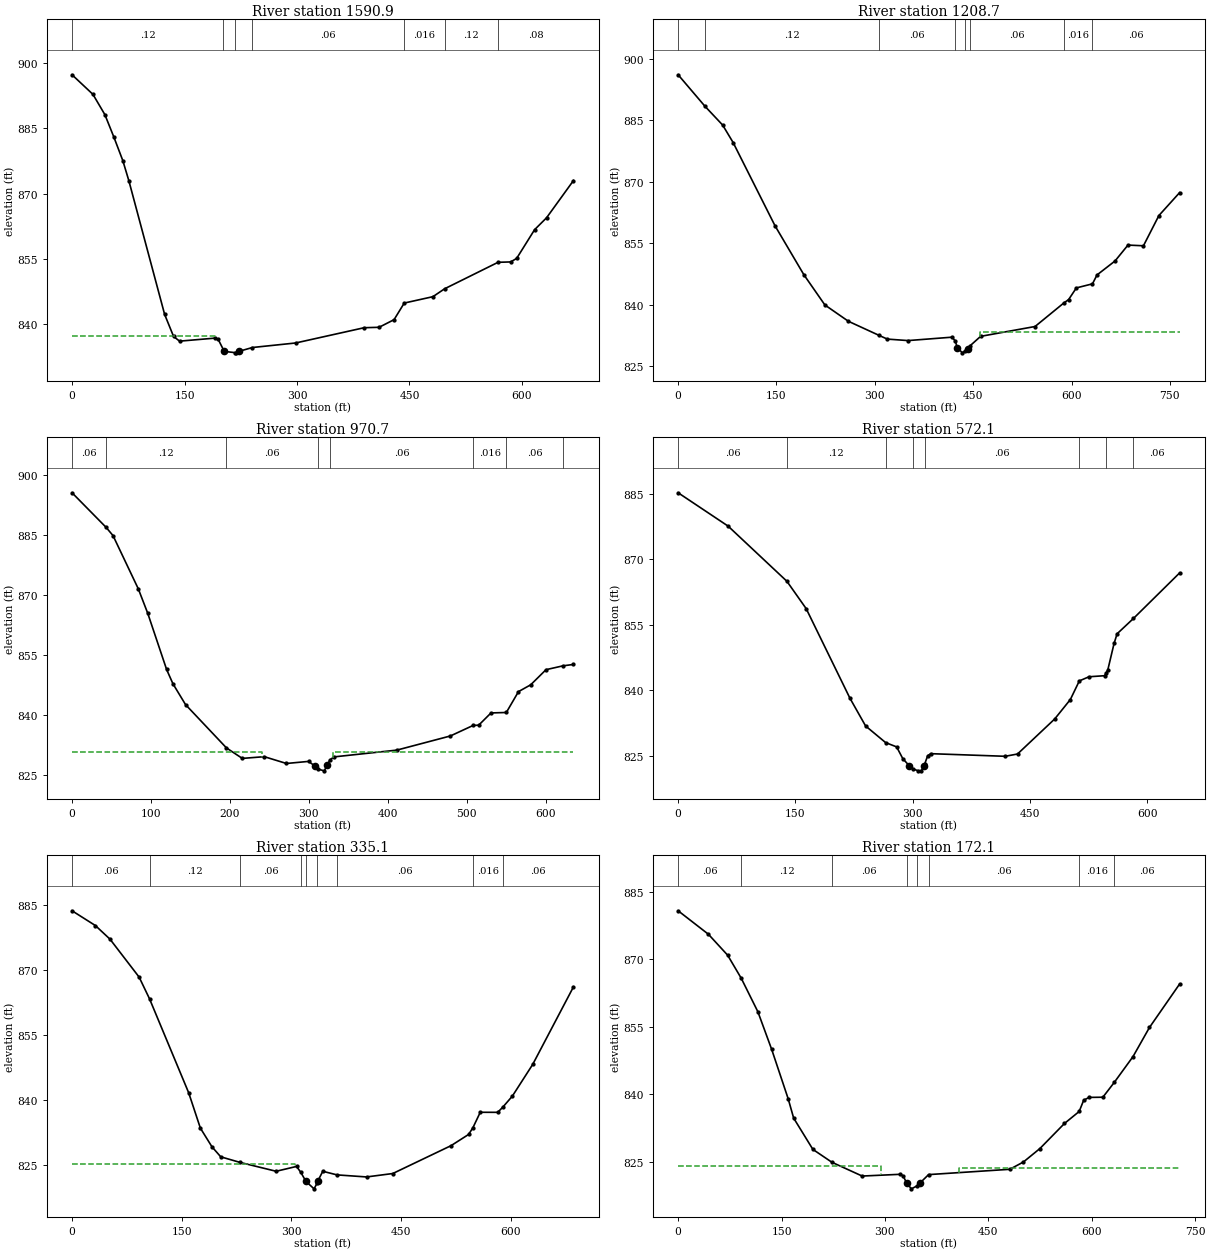
Type RM Length L Ch R = 1 ,1590.9  ,367.7,382.2,395.8
XS GIS Cut Line= 4
      2318651.26      344585.625     2318766.571      344677.418
      2318978.95      344727.769     2319134.115      344988.186
#Sta/Elev= 30
       0  897.25    27.9  892.75    43.8   888.1    55.8  882.95    67.7  877.57
    75.7  872.99   123.5  842.28   135.4  837.24   143.4  836.16     191  836.86
     195  836.54   201.8  834.22   202.9  833.81   216.8  833.54   218.8  833.48
   222.8  833.83  240.61834.7045   298.2  835.74   389.6  839.24   409.5  839.34
   429.5  841.09  443.06844.8967   481.3  846.36  496.95848.1739  568.19 854.244
     585  854.33     593  855.14   616.9  861.72   632.9  864.46   668.8     873
#Mann= 7 ,-1 , 0
       0     .12       0   201.8    .045       0   216.8     .12       0
  240.61     .06       0  443.06    .016       0  496.95     .12       0
  568.19     .08       0
#XS Ineff= 2 , 0
          190.71  837.33
Permanent Ineff=
       F       F
Bank Sta=202.9,222.8
XS Rating Curve= 0 ,0
Exp/Cntr=0.3,0.1

Type RM Length L Ch R = 1 ,1208.7  ,242,238,234.5
XS GIS Cut Line= 4
     2318277.996       344815.66     2318534.072      344859.063
     2318720.704      345073.907     2318920.357      345167.223
#Sta/Elev= 30
       0  896.11   40.85888.4445    67.9  883.85    83.9  879.58   147.8  859.28
   191.8  847.35   223.8  839.99   259.7  836.01  306.75832.5527     319  831.67
   350.6  831.31   417.8  832.14   422.7  831.19   425.7  829.57   433.6  828.32
   437.7  828.83   441.6  829.36  445.63830.0991   461.3  832.34   544.3  834.74
  588.15 840.472   595.5  841.31   607.3  844.15  631.89845.1434   638.8  847.31
   666.3  850.72     686  854.59   709.6  854.42   733.2   861.8   764.7  867.37
#Mann= 8 ,-1 , 0
       0     .06       0   40.85     .12       0  306.75     .06       0
   422.7    .045       0   437.7     .12       0  445.63     .06       0
  588.15    .016       0  631.89     .06       0
#XS Ineff= 2 , 0
                          459.86          833.38
Permanent Ineff=
       F       F
Bank Sta=425.7,441.6
XS Rating Curve= 0 ,0
Exp/Cntr=0.3,0.1

Type RM Length L Ch R = 1 ,970.7   ,393.7,398.7,406.4
XS GIS Cut Line= 3
     2318227.745      344928.602     2318616.972      345272.265
     2318667.873      345376.547
#Sta/Elev= 30
       0  895.62   43.17886.9651    51.9  884.91    83.9  871.61    95.9  865.48
   119.8  851.43   127.8  847.86   143.8  842.64  195.63831.8113   215.7  829.19
   243.6  829.62   271.6  827.92   299.6  828.44   307.5  827.31   311.5  826.52
   319.5  826.08   323.5  827.57   326.5  828.73   331.5  829.56   411.4  831.26
   479.3   834.8  508.14837.4353   515.2   837.5   530.8  840.56  550.21840.6735
   565.6  845.89   581.1   847.6   600.5  851.38  622.01852.3423   635.3  852.69
#Mann= 8 ,-1 , 0
       0     .06       0   43.17     .12       0  195.63     .06       0
   311.5    .045       0   326.5     .06       0  508.14    .016       0
  550.21     .06       0  622.01     .08       0
#XS Ineff= 2 , 0
          240.56  830.68  330.13          830.81
Permanent Ineff=
       F       F
Bank Sta=307.5,323.5
XS Rating Curve= 0 ,0
Exp/Cntr=0.3,0.1

Type RM Length L Ch R = 1 ,572.1   ,226.3,236.9,235.4
XS GIS Cut Line= 4
     2318096.789      345063.056      2318116.32      345318.047
     2318228.082      345514.445     2318364.801       345596.91
#Sta/Elev= 30
       0  885.22    63.9  877.59   139.1 864.962   163.8  858.69   219.8  838.17
   239.8  831.83  265.43828.0225   279.5  827.04   287.4  824.34   295.4  822.78
   300.3     822   307.3  821.56   311.2   821.6  314.37822.7411   315.3  823.09
   319.2  825.01   323.1  825.49   418.3  824.89   434.1  825.41   481.7  833.44
   501.7  837.89  513.19842.1565   525.6   843.1   545.6  843.34  547.62844.0117
   549.6  844.67   557.6  850.72   561.5  852.94  582.44 856.451   641.4  866.86
#Mann= 8 ,-1 , 0
       0     .06       0   139.1     .12       0  265.43     .06       0
   300.3    .045       0   315.3     .06       0  513.19    .016       0
  547.62     .12       0  582.44     .06       0
Bank Sta=295.4,314.37
XS Rating Curve= 0 ,0
Exp/Cntr=0.3,0.1

Type RM Length L Ch R = 1 ,335.1   ,162.1,163,164
XS GIS Cut Line= 2
     2317793.919      345167.213     2318096.802      345783.007
#Sta/Elev= 30
       0  883.72    31.9  880.31    51.9  877.16    91.8  868.38     106863.3723
   159.6  841.64   175.6  833.47   191.5  829.14   203.5  826.83  230.14825.5298
   279.3  823.49   307.2  824.61  313.11 823.227   320.1  821.14   331.2  819.43
   335.1  820.68  336.18821.1795   343.1  823.49  362.57822.6559     403  822.18
   438.9  822.97   518.7  829.42   542.6     832  548.49833.5346   558.6  837.13
   582.5  837.12  589.36838.2991   602.5  840.86   630.4   848.2   686.2  866.14
#Mann= 9 ,-1 , 0
       0     .06       0     106     .12       0  230.14     .06       0
  313.11     .12       0   320.1    .045       0   335.1     .12       0
  362.57     .06       0  548.49    .016       0  589.36     .06       0
#XS Ineff= 2 , 0
          305.57  825.27
Permanent Ineff=
       F       F
Bank Sta=320.1,336.18
XS Rating Curve= 0 ,0
Exp/Cntr=0.3,0.1

Type RM Length L Ch R = 1 ,172.1   ,84.5,85.1,85.5
XS GIS Cut Line= 4
     2317768.773       345198.69     2317741.646      345412.448
     2317861.003       345676.12     2318004.233      345846.476
#Sta/Elev= 30
       0  880.72    43.9  875.51    71.8  870.86   91.51 865.744   115.7  858.29
   135.7  849.94   159.6  838.99   167.6  834.67   195.5  827.72  223.18824.8554
     267   821.8   322.5  822.19   326.5  821.83   331.4  820.28   338.4  818.96
   346.4   819.6   350.3  820.17  363.36822.1216   481.1   823.3   500.9  824.92
   524.8   827.9   560.5  833.48  581.82836.1385   588.4  838.65   596.3  839.27
   616.2  839.31  632.74   842.6   659.9  848.32   683.8   854.8   727.5  864.44
#Mann= 8 ,-1 , 0
       0     .06       0   91.51     .12       0  223.18     .06       0
   331.4    .045       0   346.4     .12       0  363.36     .06       0
  581.82    .016       0  632.74     .06       0
#XS Ineff= 2 , 0
          293.91  824.05  407.02          823.65
Permanent Ineff=
       F       F
Bank Sta=331.4,350.3
XS Rating Curve= 0 ,0
Exp/Cntr=0.3,0.1

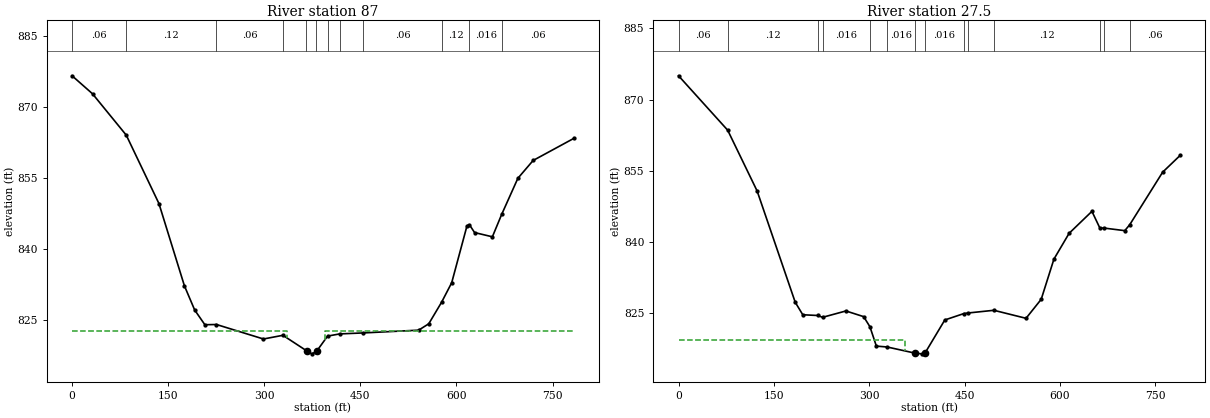
Type RM Length L Ch R = 1 ,87      ,58.7,59.5,59.8
XS GIS Cut Line= 4
     2317726.169      345214.247     2317671.377      345447.113
     2317825.109      345813.172     2317935.269      345910.559
#Sta/Elev= 30
       0  876.59    31.9  872.78    84.6864.0287   135.6  849.56   175.4  832.14
   191.4  827.03   207.3  823.92  225.43823.9641   298.8   820.9  329.12821.6827
   365.7  818.44   366.3  818.42   374.2  817.76   380.7  818.19   382.2  818.39
  398.84821.5126  417.83821.9784  454.53 822.183     541  822.77   556.8  824.12
  576.82828.6761   592.6   832.8   616.4   844.8   620.3 845.073   628.3  843.42
   656.1  842.52  670.68847.2783   695.9   854.9   719.7  858.67   783.3  863.35
#Mann= 12 ,-1 , 0
       0     .06       0    84.6     .12       0  225.43     .06       0
  329.12     .12       0   365.7    .045       0   380.7     .12       0
  398.84     .06       0  417.83     .12       0  454.53     .06       0
  576.82     .12       0   620.3    .016       0  670.68     .06       0
#XS Ineff= 2 , 0
          335.19  822.65  394.63          822.65
Permanent Ineff=
       F       F
Bank Sta=366.3,382.2
XS Rating Curve= 0 ,0
Exp/Cntr=0.3,0.1

Type RM Length L Ch R = 1 ,27.5    ,34.2,27.5,20.8
XS GIS Cut Line= 4
     2317716.855      345222.492     2317644.633      345525.269
     2317765.431      345833.788      2317875.59      345931.176
#Sta/Elev= 30
       0  875.01   77.33863.5399   123.7  850.71   183.6  827.27   195.5  824.63
  218.78824.4754  226.72824.0922   263.4  825.43   291.3  824.23  301.17 822.102
   311.3  818.02  328.32817.8336   372.7  816.52   383.1  816.39   387.7  816.52
     419  823.53  448.61824.8622  455.46825.0004  496.26825.5692   546.8  823.88
   570.7  827.89   590.7  836.36   614.6   841.8   650.5  846.43  662.99842.9086
  669.88842.8996   702.2  842.36  710.02843.6186   761.8  854.69   789.6  858.26
#Mann= 14 ,-1 , 0
       0     .06       0   77.33     .12       0  218.78     .06       0
  226.72    .016       0  301.17     .12       0  328.32    .016       0
   372.7    .045       0   387.7    .016       0  448.61     .06       0
  455.46    .016       0  496.26     .12       0  662.99     .08       0
  669.88    .016       0  710.02     .06       0
#XS Ineff= 2 , 0
          355.83  819.34
Permanent Ineff=
       F       F
Bank Sta=372.7,387.7
XS Rating Curve= 0 ,0
Exp/Cntr=0.3,0.1

Chan Stop Cuts=-1
Use User Specified Reach Order=0
Composite Channel Slope=5